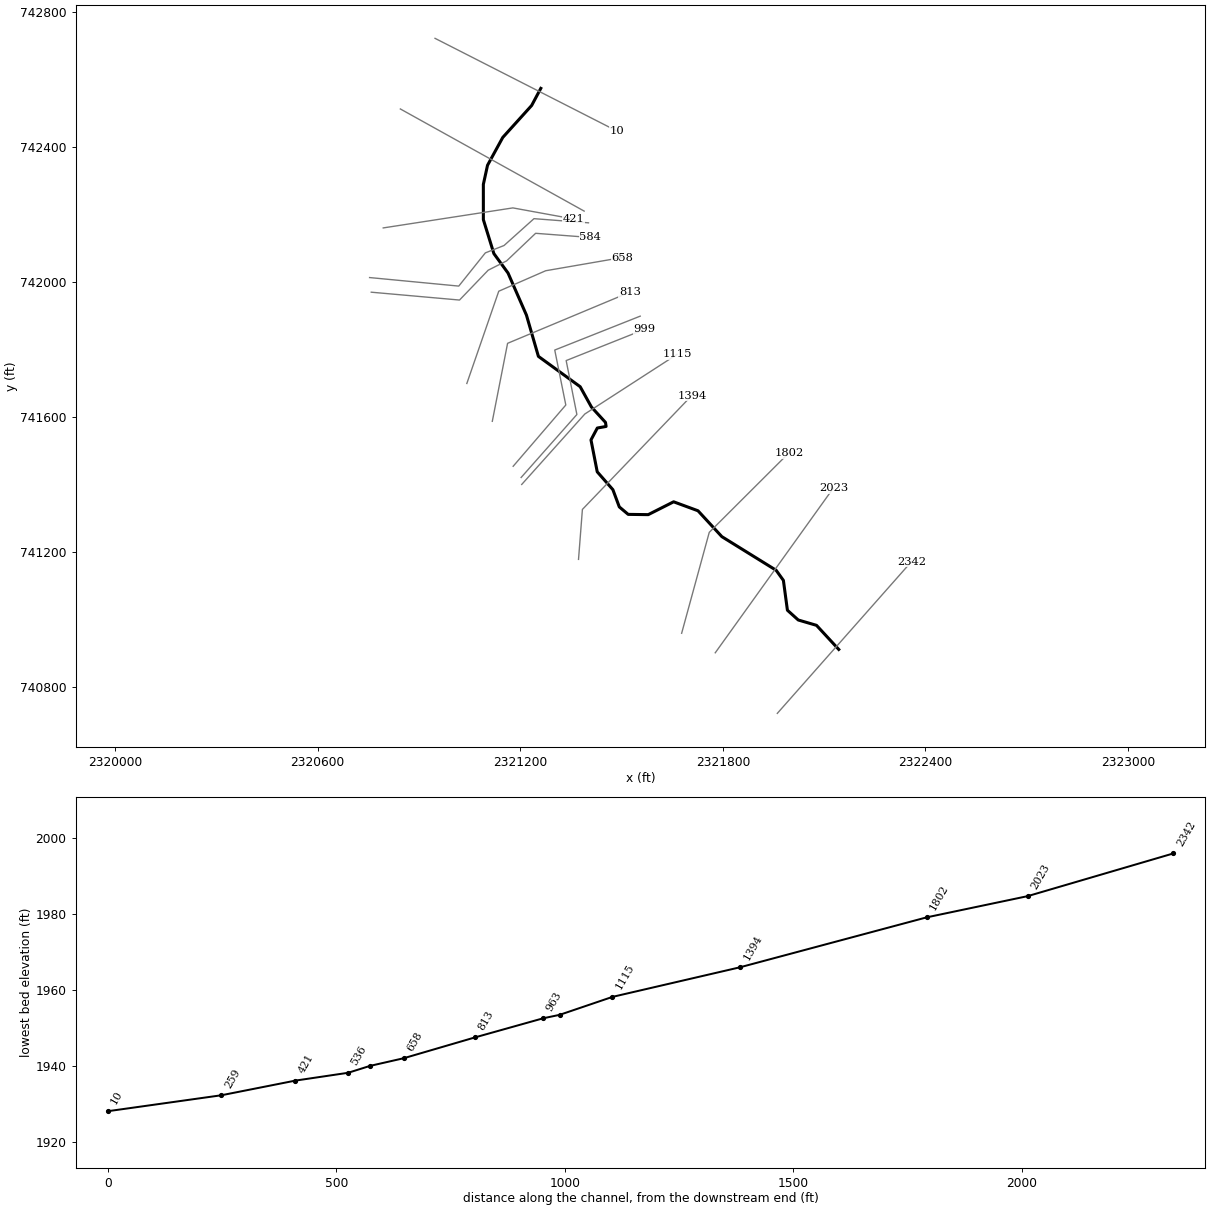
--- SLABCMPRN.prj (project) ---

Proj Title=SLABCMPRN
Current Plan=p01
Default Exp/Contr=0,0
English Units
Geom File=g01
Flow File=f01
Plan File=p01
BEGIN DESCRIPTION:
----------MODEL BY WOOD PLC 2022----------
AFH study
Randolph County, WV
HEC-RAS Version: RAS 6.2
Vertical Datum: NAVD88
Projection: NAD 1983 StatePlane West Virginia S FIPS 4702 (US Feet)
Terrain: 1-meter LIDAR (FEMA Region III 3DEP collected 2016-2018)
Land Use: 2019 NLCD
Hydrologic Method:
WV SIR2010-5033 regression equations
Additional Model Notes:
Normal depth tie in to Tucker County.
END DESCRIPTION:
DSS Export Rating Curves= 0
DSS Export Rating Curve Sorted= 0
DSS Export Volume Flow Curves= 0
DXF OffsetX= 0
DXF OffsetY= 0
DXF ScaleX= 0
DXF ScaleY= 0

--- SLABCMPRN.p01 (plan) ---

Plan Title=Floodplain
Program Version=6.20
Short Identifier=Floodplain
Geom File=g01
Flow File=f01
Subcritical Flow
K Sum by GR= 0
Std Step Tol= 0.01
Critical Tol= 0.01
Num of Std Step Trials= 20
Max Error Tol= 0.3
Flow Tol Ratio= 0.001
Split Flow NTrial= 30
Split Flow Tol= 0.02
Split Flow Ratio= 0.02
Log Output Level= 0
Friction Slope Method= 1
Unsteady Friction Slope Method= 2
Unsteady Bridges Friction Slope Method= 1
Parabolic Critical Depth
Global Vel Dist= 0 , 0 , 0
Global Log Level= 0
CheckData=True
Encroach Param=-1 ,0,0, 0
Mapping Interval=1HOUR
Computation Time Step Use Courant=        0
Computation Time Step Use Time Series=    0
Computation Time Step Count To Double=0
Computation Time Step Max Doubling=0
Computation Time Step Max Halving=0
Computation Time Step Residence Courant=0
Run HTab= 0
Run UNet= 0
Run Sediment= 0
Run PostProcess= 0
Run WQNet= 0
Run RASMapper=-1
UNET Theta= 0
UNET Theta Warmup= 0
UNET ZTol= 0
UNET ZSATol= 0
UNET MxIter= 0
UNET Max Iter WO Improvement= 0
UNET MaxInSteps= 0
UNET DtIC= 0
UNET DtMin= 0
UNET MaxCRTS= 0
UNET WFStab= 0
UNET SFStab= 0
UNET WFX= 1
UNET SFX= 1
UNET Gravity=32.174
UNET 1D Methodology=Finite Difference
UNET DSS MLevel= 1
UNET Pardiso=0
UNET DZMax Abort= 0
UNET Use Existing IB Tables= 0
UNET Froude Reduction=False
UNET Froude Limit= 0
UNET Froude Power= 0
UNET D1 Cores= 0
UNET WindReference=Eulerian
UNET WindDragFormulation=Hsu (1988)
UNET D2 Coriolis=0
UNET D2 Cores= 0
UNET D2 Theta= 1
UNET D2 Theta Warmup= 1
UNET D2 Z Tol= 0.01
UNET D2 Volume Tol= 0.01
UNET D2 Max Iterations= 20
UNET D2 Equation= 0
UNET D2 RampUpFraction=0.1
UNET D2 TimeSlices= 1
UNET D2 Turbulence Formulation=Non-Conservative (original)
UNET D2 Eddy Viscosity=0.3
UNET D2 Transverse Eddy Viscosity=0.1
UNET D2 Smagorinsky Mixing=0
UNET D2 BCVolumeCheck=0
UNET D2 Cores=0
UNET D2 SolverType=PARDISO (Direct)
UNET D2 Minimum Iterations= 2147483647
UNET D2 Maximum Iterations= 2147483647
UNET D2 Restart Number= 10
UNET D2 Relaxation Coeff=1.3
UNET D2 SOR Precondition Iterations= 10
UNET D2 ILUT Maximum Fill= 8
UNET D2 ILUT Tolerance=1E-08
UNET D1D2 MaxIter= 0
UNET D1D2 ZTol=0.01
UNET D1D2 QTol=0.1
UNET D1D2 MinQTol=1
Write IC File= 0
Write IC File at Fixed DateTime=0
Write IC File at Sim End=0
Echo Input=False
Echo Parameters=False
Echo Output=False
Write Detailed= 0
HDF Write Warmup=0
HDF Write Time Slices=0
HDF Flush=0
HDF Compression= 1
HDF Chunk Size= 1
HDF Spatial Parts= 1
HDF Use Max Rows=0
HDF Fixed Rows= 1
Calibration Method= 0
Calibration Iterations= 20
Calibration Max Change=0.05
Calibration Tolerance=0.2
Calibration Maximum=1.5
Calibration Minimum=0.5
Calibration Optimization Method= 1
WQ AD Non Conservative
WQ ULTIMATE=-1
WQ Max Comp Step=1HOUR
WQ Output Interval=15MIN
WQ Output Selected Increments= 0
WQ Output face flow=0
WQ Output face velocity=0
WQ Output face area=0
WQ Output face dispersion=0
WQ Output cell volume=0
WQ Output cell surface area=0
WQ Output cell continuity=0
WQ Output cumulative cell continuity=0
WQ Output face conc=0
WQ Output face dconc_dx=0
WQ Output face courant=0
WQ Output face peclet=0
WQ Output face adv mass=0
WQ Output face disp mass=0
WQ Output cell mass=0
WQ Output cell source sink temp=0
WQ Output nsm pathways=0
WQ Output nsm derived pathways=0
WQ Create Restart=0
WQ Fixed Restart=0
WQ System Summary=0
WQ Write To DSS=0
Sorting and Armoring Iterations= 10
XS Update Threshold= 0.02
Bed Roughness Predictor= 0
Hydraulics Update Threshold= 0.02
Energy Slope Method= 1
Volume Change Method= 1
Sediment Retention Method= 0
Sediment TS Multiplier= 1
Warm Up Method= 0
XS Weighting Method= 0
Number of US Weighted Cross Sections= 1
Number of DS Weighted Cross Sections= 1
Upstream XS Weight=0
Main XS Weight=1
Downstream XS Weight=0
Number of DS XS's Weighted with US Boundary= 1
Upstream Boundary Weight= 1
Weight of XSs Associated with US Boundary= 0
Number of US XS's Weighted with DS Boundary= 1
Downstream Boundary Weight= 0.5
Weight of XSs Associated with DS Boundary= 0.5
Percentile Method= 0
Sediment Output Level= 3
Mass or Volume Output= 0
Output Increment Type= 1
Profile and TS Output Increment= 1
Transport Output Increment 1
XS Output Flag= 0
XS Output Increment= 10
Read HDF5 Sediment Hotstart= 0
Sediment Hotstart Type= 0
Write Gradation File= 0
Read Gradation Hotstart= 0
Write HDF5 File= 1
Write Binary Output= 1
Write DSS Sediment File= 0
DSS Sediment Output Type= 1
SV Curve= 0
Specific Gage Flag= 0
Subcell Erosion Methods= 0
Subcell Deposition Methods= 0
Advection Scheme= 1
Matrix Solver= 0
Implicit Weighting Factor= 1
Maximum Outer Loop Convergence Iterations= 5
Convergence Maximum Absolute= 0.001
Convergence RMSE= 0.0001
Grain Fractions Max Abs Error= 0.001
Max Subgrid Regions= 1
Max Subgrid Length Scale= 3.402823E+38
Initial Layer Thickness= 3.402823E+38
Min Layer Thickness= 3.402823E+38
Max Layer Thickness= 3.402823E+38
Number of Layers= 5

--- SLABCMPRN.f01 (steady flow) ---

Flow Title=Flow
Program Version=6.20
Number of Profiles= 1
Profile Names=P100yr
River Rch & RM=SLABCMPRN,Main,2342
     347
River Rch & RM=SLABCMPRN,Main,813
     612
Boundary for River Rch & Prof#=SLABCMPRN,Main            , 1
Up Type= 0
Dn Type= 3
Dn Slope=0.01683
DSS Import GetInterval= 0
DSS Import GetPeak= 0
DSS Import FillOption= 0

--- SLABCMPRN.g01 (geometry) ---

Geom Title=Geometry
Program Version=6.20

River Reach=SLABCMPRN       ,Main
Reach XY= 30
     2322143.322      740911.511     2322077.436      740982.865
      2322023.27      740998.751     2321991.238      741027.657
     2321979.346      741116.025     2321957.862      741145.973
     2321797.054      741245.583     2321726.421      741322.188
     2321654.285      741348.751     2321579.025       741310.73
      2321519.65      741311.511     2321493.348      741333.647
     2321474.338      741384.688     2321427.983      741437.553
     2321409.494      741532.084     2321428.244       741567.24
     2321454.285      741571.928     2321452.462      741583.907
     2321410.796       741629.48     2321377.462      741689.636
     2321253.765       741779.48     2321218.348      741901.615
     2321163.834      742026.268     2321121.886      742083.845
     2321090.754      742184.383     2321090.716      742288.779
     2321103.079       742345.37     2321148.188      742427.831
     2321233.772      742522.529     2321260.855      742573.223

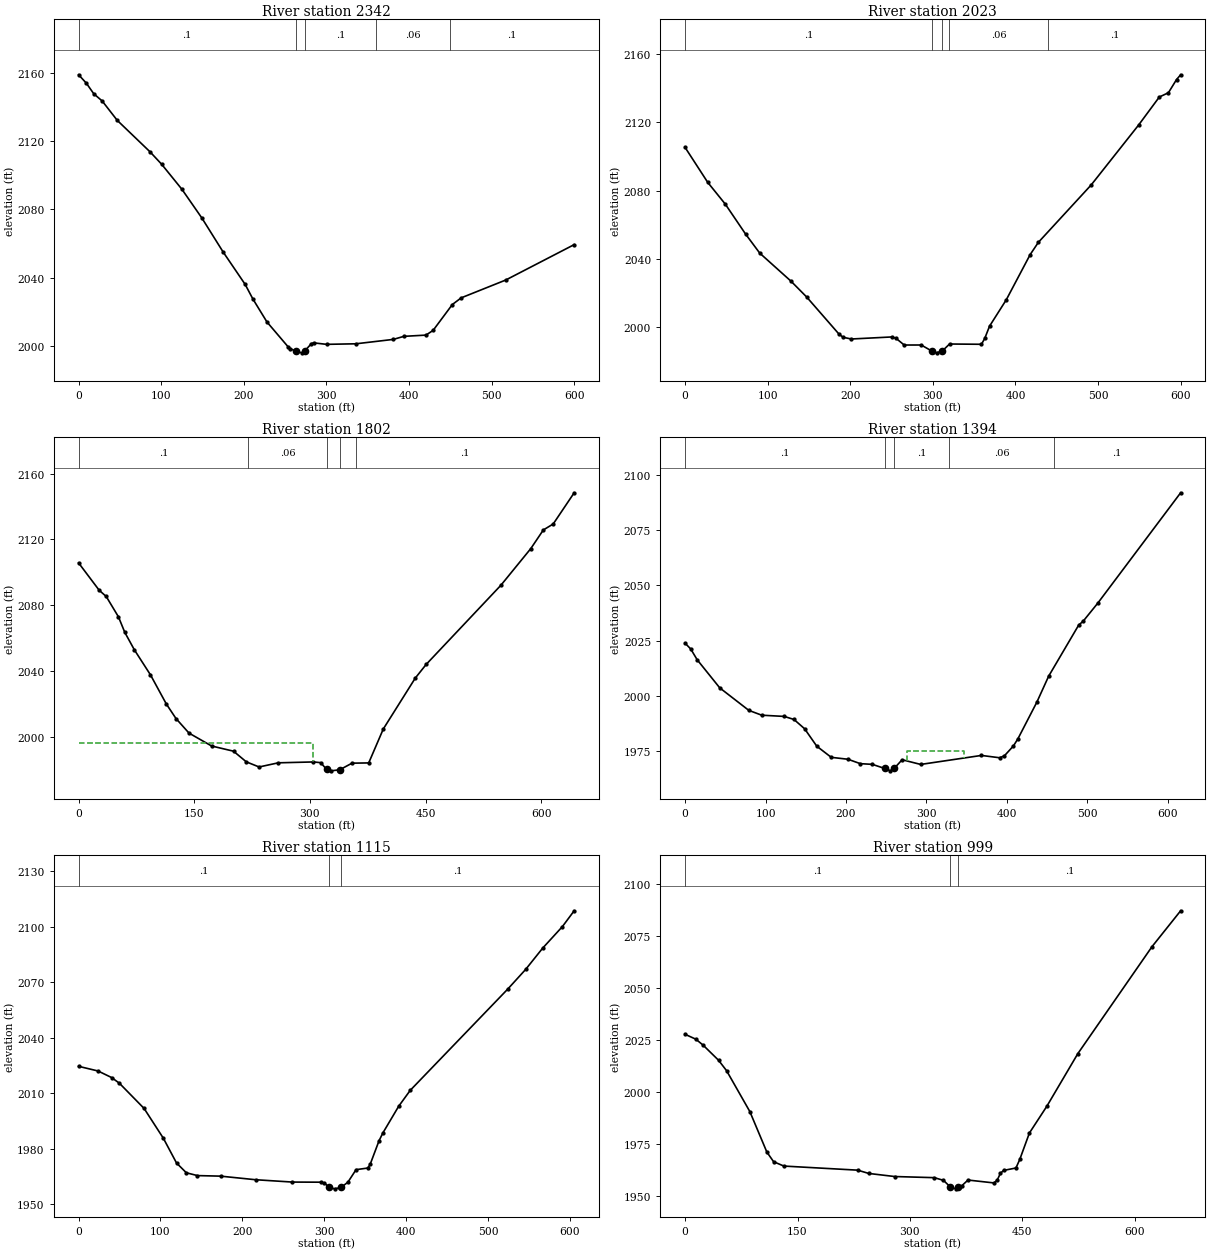
Type RM Length L Ch R = 1 ,2342    ,318.9,318.9,318.9
XS GIS Cut Line= 2
2321961.31802368740722.1468720072322358.71979634741171.670877023
#Sta/Elev= 30
       0 2158.73     9.4 2153.78    18.3 2147.63    28.5 2143.41    46.8 2132.04
    86.4 2113.68   100.5 2106.39   125.1 2091.71   149.3 2074.87   174.9 2055.09
   201.6 2036.12     211 2027.54     228 2014.12   253.5 1999.65   256.4 1998.36
  262.791997.176     270 1996.05  273.811997.174   281.9 2001.47   284.7 2001.88
   300.2 2001.02   335.7 2001.34   381.1 2003.92   393.8  2005.7   420.5 2006.42
   429.2 2009.18   452.5 2024.32   463.2 2028.22   517.1 2038.64     600 2059.36
#Mann= 5 ,-1,0
       0      .1       0  262.79    .045       0  273.81      .1       0
     360     .06       0     450      .1       0
Bank Sta=262.79,273.81
XS Rating Curve= 0 ,0
Exp/Cntr(USF)=0,0
Exp/Cntr=0.3,0.1

Type RM Length L Ch R = 1 ,2023    ,220.9,220.9,220.9
XS GIS Cut Line= 2
2321777.55186509740901.616082335 2322127.2014956741389.207238817
#Sta/Elev= 30
       0 2105.31    27.4 2084.82    48.7 2072.03    73.2 2054.51    90.4 2043.29
   128.1 2026.89   147.1  2017.6   186.5 1995.69   191.4  1993.9   201.3 1992.91
   250.5 1994.12   255.4 1993.31   265.3 1989.37   285.9 1989.39  298.441985.919
   304.6 1984.79  311.491985.919   320.2 1989.97   358.8 1989.81   362.8 1993.22
   368.6 2000.42   388.9 2015.93   417.8 2042.43   427.7 2049.61   491.7 2083.31
   549.1 2118.46   574.2 2134.91   585.2 2137.41     595 2145.12     600 2147.95
#Mann= 5 ,-1,0
       0      .1       0  298.44    .045       0  311.49      .1       0
     320     .06       0     440      .1       0
Bank Sta=298.44,311.49
XS Rating Curve= 0 ,0
Exp/Cntr(USF)=0,0
Exp/Cntr=0.3,0.1

Type RM Length L Ch R = 1 ,1802    ,408.1,408.1,408.1
XS GIS Cut Line= 3
2321677.99384217740959.4023850592321759.77152264741258.294155117
2321995.46440828741493.435143676
#Sta/Elev= 30
       0 2105.64    26.7 2089.01    35.8 2085.24    51.6 2072.91    59.9 2063.41
    72.3  2052.8    93.1 2037.65   113.8 2019.83   126.3 2011.01   143.2 2002.14
   172.5 1994.31   200.9 1991.15   217.5 1984.67   234.1 1981.55     259 1984.08
   304.6 1984.61     314 1984.18   321.7 1980.06   327.4  1979.2   338.7 1979.85
   354.6 1983.86   376.3 1984.02   395.2 2004.66   436.7 2035.62   450.8 2043.92
   547.8  2092.1   586.6 2114.42   602.8 2125.71   615.6 2129.34   642.8 2148.32
#Mann= 5 ,-1,0
       0      .1       0     220     .06       0   321.7    .045       0
   338.7     .06       0     360      .1       0
#XS Ineff= 2 , 0
           304.3 1996.03
Permanent Ineff=
       F       F
Bank Sta=321.7,338.7
XS Rating Curve= 0 ,0
Exp/Cntr(USF)=0,0
Exp/Cntr=0.3,0.1

Type RM Length L Ch R = 1 ,1394    ,279,279,279
XS GIS Cut Line= 3
2321372.56191357741178.2020836162321384.08025187741326.170130021
2321707.98276296 741663.47743134
#Sta/Elev= 30
       0 2023.79       7 2021.19      15 2016.31    43.1 2003.58    79.2 1993.41
    95.3 1991.22   123.3 1990.67   135.4 1989.28   148.6 1985.08   163.7  1977.2
   181.7 1972.16   202.5 1971.29   217.9 1969.29   232.7 1968.99  248.27 1967.12
   255.3 1966.05  259.881967.122   269.8 1971.07   292.9 1968.95   368.4 1973.02
     391 1971.97   396.9 1972.83   408.1 1977.28   413.7 1980.51   437.3 1997.12
     452 2008.89   489.3 2031.98   495.1 2033.84   513.1 2041.94616.0577 2091.85
#Mann= 5 ,-1,0
       0      .1       0  248.27    .045       0  259.88      .1       0
  328.42     .06       0  458.42      .1       0
#XS Ineff= 1 ,-1
275.5706346.7996    1975
Permanent Ineff=
       F
Bank Sta=248.27,259.88
XS Rating Curve= 0 ,0
Exp/Cntr(USF)=0,0
Exp/Cntr=0.3,0.1

Type RM Length L Ch R = 1 ,1115    ,115.5,115.5,115.5
XS GIS Cut Line= 3
2321204.34790849741400.1090857712321391.24770158741608.772432714
2321664.32166257 741785.36762956
#Sta/Elev= 30
       0 2024.54    23.7 2022.02    40.3 2018.47    49.8 2015.39      80 2001.73
   103.5 1985.62   119.6 1972.22   131.6 1966.94   145.1 1965.42   173.4 1965.12
   216.2 1963.18   261.2 1961.91   295.5 1961.85   300.3  1961.4     3061959.026
   312.9 1958.25  320.541959.025   328.9 1961.83   338.9 1968.63   353.4 1969.51
   356.3 1971.72     367 1984.31   371.7 1988.53     391 2002.96   405.1 2011.56
   524.2 2066.34   546.1    2077     567 2088.57   590.9 2100.13605.3287 2108.71
#Mann= 3 ,-1,0
       0      .1       0     306    .045       0  320.54      .1       0
Bank Sta=306,320.54
XS Rating Curve= 0 ,0
Exp/Cntr(USF)=0,0
Exp/Cntr=0.3,0.1

Type RM Length L Ch R = 1 ,999     ,36.1,36.1,36.1
XS GIS Cut Line= 4
2321202.60262282741420.7536670152321367.71389876741607.285608233
2321335.97233577741767.017344538 2321567.6057237741859.250402995
#Sta/Elev= 30
       0 2027.81    14.4 2025.45    24.1 2022.58    44.6 2015.36    55.3 2010.35
    86.4 1990.67   109.1  1971.2   118.1 1966.56   131.8 1964.47   230.3  1962.5
   245.1 1960.92   279.6 1959.44   332.6 1958.89   344.8  1957.6  353.461954.587
   361.2 1953.52  364.581954.588   369.3 1955.01   377.5 1957.75   412.2 1956.36
   416.5  1957.7   420.8    1961   425.1 1962.38   441.5 1963.54   446.6 1967.65
   459.5 1980.38   482.7  1993.2   524.1 2018.52   623.1 2069.96661.2863  2087.2
#Mann= 3 ,-1,0
       0      .1       0  353.46    .045       0  364.58      .1       0
Bank Sta=353.46,364.58
XS Rating Curve= 0 ,0
Exp/Cntr(USF)=0,0
Exp/Cntr=0.3,0.1

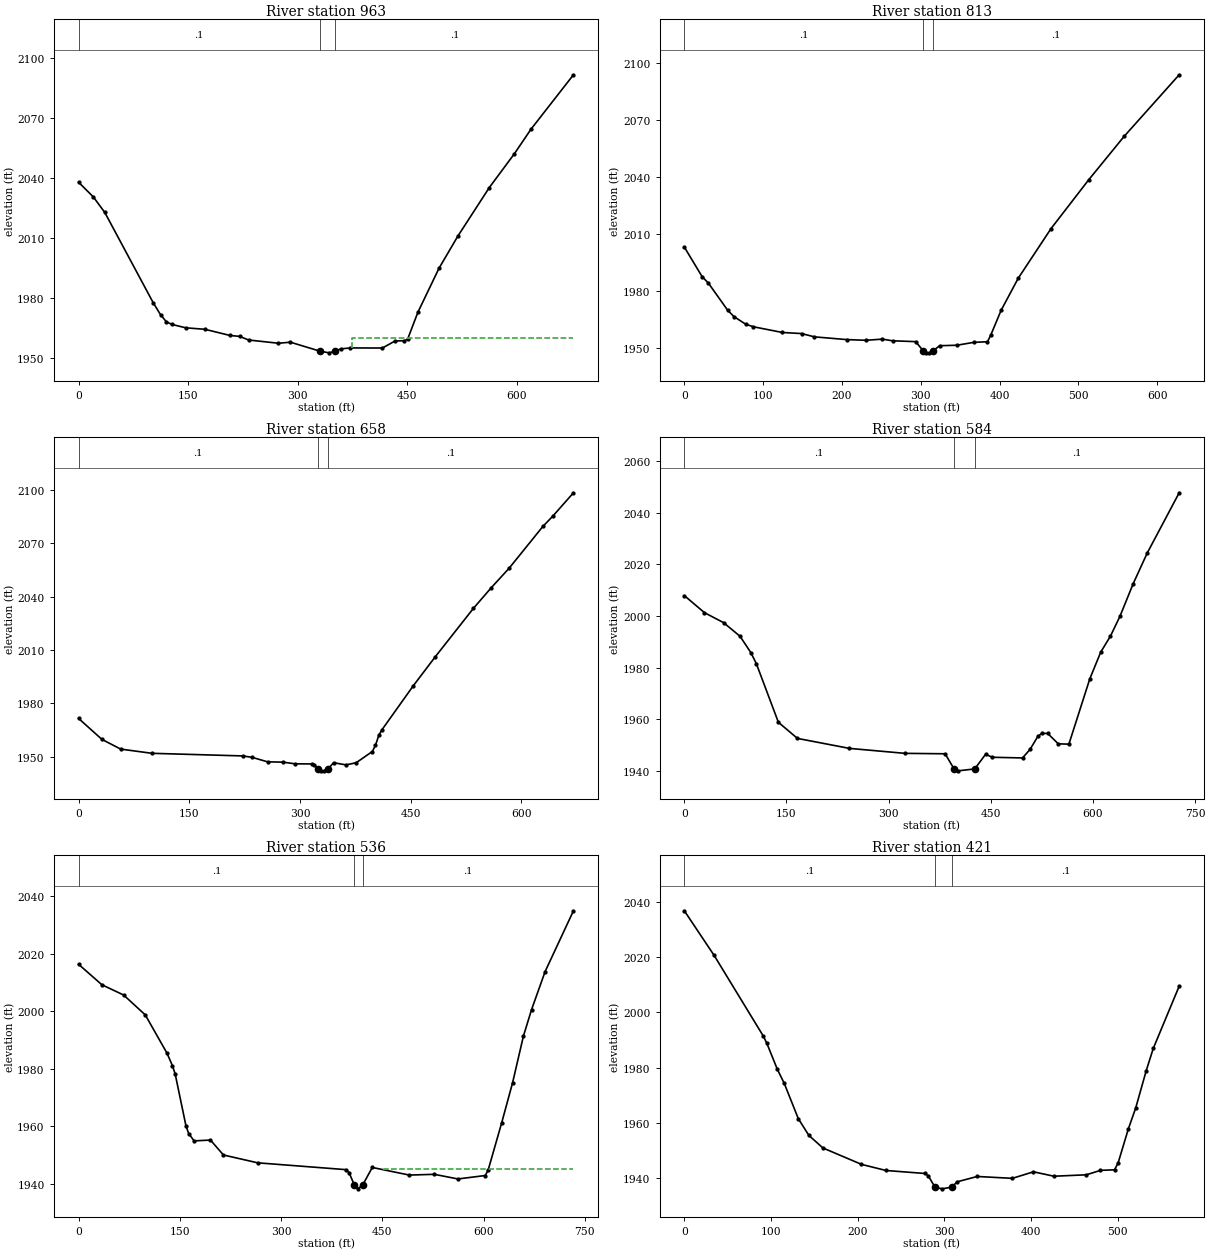
Type RM Length L Ch R = 1 ,963     ,149.8,149.8,149.8
XS GIS Cut Line= 4
2321179.03604186 741453.982054482321334.93202532741635.394388765
2321302.16654095 741798.19788923  2321555.302278741898.622318779
#Sta/Elev= 30
       0 2037.91    20.2 2030.57    35.9 2022.79   102.4  1977.5   112.2  1971.7
   120.2 1968.12   127.9 1966.81   146.6 1965.13     173 1964.38   207.3  1961.3
   220.5 1960.84   232.8 1959.03   273.6 1957.41     290 1957.93  330.521953.444
     343 1952.61  351.441953.444   359.3  1954.6   372.1 1955.06     416 1955.02
   433.2 1958.52   446.2 1958.69   450.5 1959.43   464.6 1972.92   493.5 1994.92
   519.3 2010.98   562.3 2035.23   596.8 2052.22   619.4 2064.43677.5908 2091.66
#Mann= 3 ,-1,0
       0      .1       0  330.52    .045       0  351.44      .1       0
#XS Ineff= 2 , 0
                             375            1960
Permanent Ineff=
       F       F
Bank Sta=330.52,351.44
XS Rating Curve= 0 ,0
Exp/Cntr(USF)=0,0
Exp/Cntr=0.3,0.1

Type RM Length L Ch R = 1 ,813     ,155.1,155.1,155.1
XS GIS Cut Line= 3
2321117.23410329741587.1396159422321162.49202161741818.111061168
2321524.55536818741969.490994863
#Sta/Elev= 30
       0 2003.19    22.5 1987.68    30.6 1984.18    55.1  1969.9    63.2 1966.55
    77.7 1962.65    87.7 1961.26   124.4 1958.26   148.8 1957.69   165.1 1955.95
   205.9 1954.52   230.3 1954.15   251.2 1954.76   264.1 1953.89   293.5 1953.44
  303.251948.527   306.6 1947.68   310.9 1947.55  315.451948.527   323.9  1951.3
   345.6 1951.54   367.4 1953.08   384.6 1953.38   388.8 1956.92   401.9 1969.93
   423.6 1986.79   465.2 2012.89   512.9 2038.52     558 2061.43627.7994 2093.81
#Mann= 3 ,-1,0
       0      .1       0  303.25    .045       0  315.45      .1       0
Bank Sta=303.25,315.45
XS Rating Curve= 0 ,0
Exp/Cntr(USF)=0,0
Exp/Cntr=0.3,0.1

Type RM Length L Ch R = 1 ,658     ,74,74,74
XS GIS Cut Line= 4
2321041.80778998741699.1773823172321136.33181766741972.407849406
2321275.38287016742033.0846723142321501.90023012 742072.24282818
#Sta/Elev= 30
       0 1971.55    31.7 1959.75    57.1 1954.31    99.5 1951.95   222.2 1950.48
   234.9 1949.71   256.1 1947.16   277.2 1946.97   293.3 1946.04   316.9 1945.96
   319.5 1945.62  324.361943.032   328.2 1942.17   332.1 1942.09  337.551943.032
   345.7 1946.65   362.5 1945.44   376.2 1946.64   398.1 1952.95   402.4 1956.47
   406.8 1961.98   411.1 1965.16   453.8 1990.04   483.1 2006.07     535 2033.42
   559.3 2045.09   583.5 2056.04   629.2 2079.52   642.9 2085.43 670.709 2098.48
#Mann= 3 ,-1,0
       0      .1       0  324.36    .045       0  337.55      .1       0
Bank Sta=324.36,337.55
XS Rating Curve= 0 ,0
Exp/Cntr(USF)=0,0
Exp/Cntr=0.3,0.1

Type RM Length L Ch R = 1 ,584     ,47.7,47.7,47.7
XS GIS Cut Line= 6
2320758.70782479741969.534240642 2321020.1206858741946.274625638
2321105.08765889 742034.709638452321159.58397702742062.214164383
2321245.54326748 742143.952889572321406.98331079742131.651435603
#Sta/Elev= 30
       0 2007.88    29.6 2001.27    57.7  1997.4    81.8 1992.14    97.9 1985.73
   105.9 1981.44   138.1 1958.86   166.1 1952.61   242.4 1948.75   323.9 1946.83
     383 1946.66  396.081940.797     402 1940.06   426.41940.797   442.3 1946.43
   452.5 1945.31   496.6 1945.05   507.7 1948.38   519.4 1953.52     525 1954.53
   533.5 1954.55   549.1 1950.51   564.7 1950.39   595.5 1975.74   611.5 1986.03
   625.7 1992.19   639.6 1999.82   659.2 2012.54   679.7 2024.34726.6536 2047.67
#Mann= 3 ,-1,0
       0      .1       0  396.08    .045       0   426.4      .1       0
Bank Sta=396.08,426.4
XS Rating Curve= 0 ,0
Exp/Cntr(USF)=0,0
Exp/Cntr=0.3,0.1

Type RM Length L Ch R = 1 ,536     ,115.4,115.4,115.4
XS GIS Cut Line= 6
2320753.80593227742012.8847371192321017.90597257741987.609737649
2321096.61557326742085.9938974122321152.04690266742107.833298676
2321240.64137496742187.3033860462321402.08141828742175.001932079
#Sta/Elev= 30
       0 2016.36    34.5 2009.24    66.7 2005.68    98.8 1998.75     131 1985.42
     139 1981.08     143 1978.27   159.1 1960.09   163.1 1957.47   171.1 1954.93
   195.3 1955.22   214.6 1950.02   265.3  1947.3   396.4 1944.92   400.7 1943.87
  408.341939.639   413.6 1938.25  420.971939.641     435 1945.69   489.9 1943.04
   526.8  1943.3   561.9 1941.69   602.5 1942.89   606.8  1944.9   626.8 1961.29
   642.9 1975.21   658.9 1991.38   670.9 2000.55     691 2013.82733.0292 2034.98
#Mann= 3 ,-1,0
       0      .1       0  408.34    .045       0  420.97      .1       0
#XS Ineff= 2 , 0
                        451.7248            1945
Permanent Ineff=
       F       F
Bank Sta=408.34,420.97
XS Rating Curve= 0 ,0
Exp/Cntr(USF)=0,0
Exp/Cntr=0.3,0.1

Type RM Length L Ch R = 1 ,421     ,161.8,161.8,161.8
XS GIS Cut Line= 3
2320794.18620355742159.8863753872321178.09820034742219.189854566
2321357.56925575 742186.41687923
#Sta/Elev= 30
       0 2036.67    34.4 2020.54    91.1  1991.4    95.1 1988.85   107.2 1979.47
   115.3 1974.29   131.5 1961.55   143.7 1955.49   159.9 1950.96   204.4 1945.03
   232.7 1942.82   277.2 1941.75   281.3    1941  289.121936.794   297.4 1936.19
  308.271936.794   314.9 1938.74   337.9 1940.66   378.4 1939.98   402.8 1942.34
   426.4 1940.75   463.8 1941.26     480 1942.86   496.3 1943.07   500.4 1945.49
   512.3  1957.9   520.7 1965.37   532.9 1978.91     541 1986.93570.9042 2009.43
#Mann= 3 ,-1,0
       0      .1       0  289.12    .045       0  308.27      .1       0
Bank Sta=289.12,308.27
XS Rating Curve= 0 ,0
Exp/Cntr(USF)=0,0
Exp/Cntr=0.3,0.1

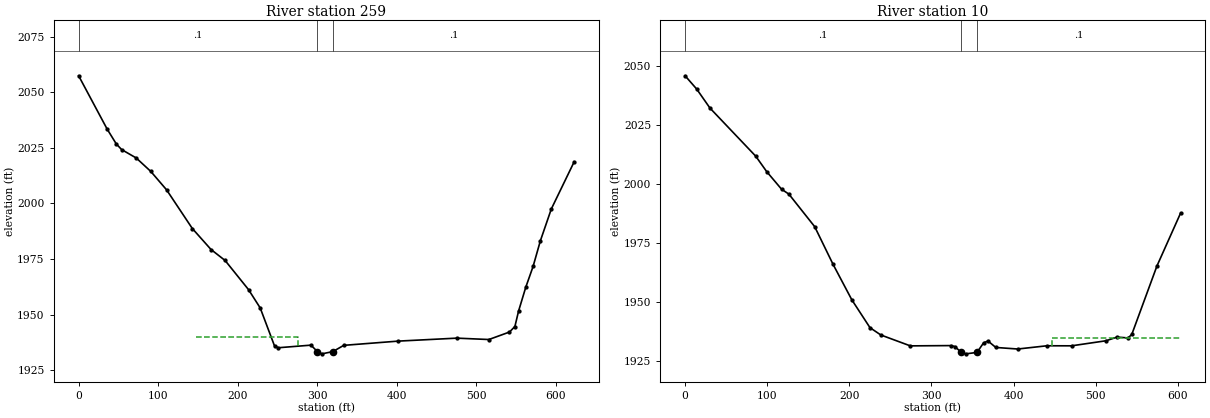
Type RM Length L Ch R = 1 ,259     ,248.8,248.8,248.8
XS GIS Cut Line= 2
2320844.89393816742512.2165577572321389.26625587742209.718708161
#Sta/Elev= 30
       0 2057.41    35.8 2033.45    47.4 2026.71    54.1  2024.2    72.4 2020.43
    90.7 2014.38   110.5 2006.12   142.9  1988.7   166.4 1979.26   184.1 1974.32
   213.5 1961.23   228.2 1952.98   246.3 1935.79   250.9 1935.07     292 1936.24
  300.141933.332   305.8 1932.33  319.471933.331   333.2 1936.15   401.5 1938.05
   475.3 1939.39   515.6 1938.77   541.5 1942.14   548.3 1944.62   552.9 1951.55
     562 1962.32   571.2 1971.68   580.3 1983.16   594.1 1997.52   622.8 2018.73
#Mann= 3 ,-1,0
       0      .1       0  300.14    .045       0  319.47      .1       0
#XS Ineff= 1 ,-1
147.2239275.2583    1940
Permanent Ineff=
       F
Bank Sta=300.14,319.47
XS Rating Curve= 0 ,0
Exp/Cntr(USF)=0,0
Exp/Cntr=0.3,0.1

Type RM Length L Ch R = 1 ,10      ,,,
XS GIS Cut Line= 2
2320947.59201878742721.3815026332321485.13817509742447.406364903
#Sta/Elev= 30
       0 2045.73    14.1 2040.12    30.3 2032.06      86 2011.72    99.4 2005.17
   117.4 1997.77   126.4 1995.66   157.8  1981.9   180.2 1965.94     203 1950.97
   225.1 1939.19   238.3  1936.1   274.2 1931.49   323.9 1931.61   328.4  1931.2
  336.361928.719   341.9 1928.12   355.41928.717   363.4 1932.76   368.8 1933.55
   378.3 1930.82     405 1930.16   440.6 1931.53   470.5 1931.51   512.5 1933.65
   525.9  1935.2   539.4 1934.85   543.9 1936.36   574.5 1965.29603.3392 1987.69
#Mann= 3 ,-1,0
       0      .1       0  336.36    .045       0   355.4      .1       0
#XS Ineff= 2 , 0
                          447.24         1934.88
Permanent Ineff=
       F       F
Bank Sta=336.36,355.4
XS Rating Curve= 0 ,0
Exp/Cntr(USF)=0,0
Exp/Cntr=0.3,0.1
LCMann Table=0

Chan Stop Cuts=-1
Use User Specified Reach Order=0
Composite Channel Slope=5